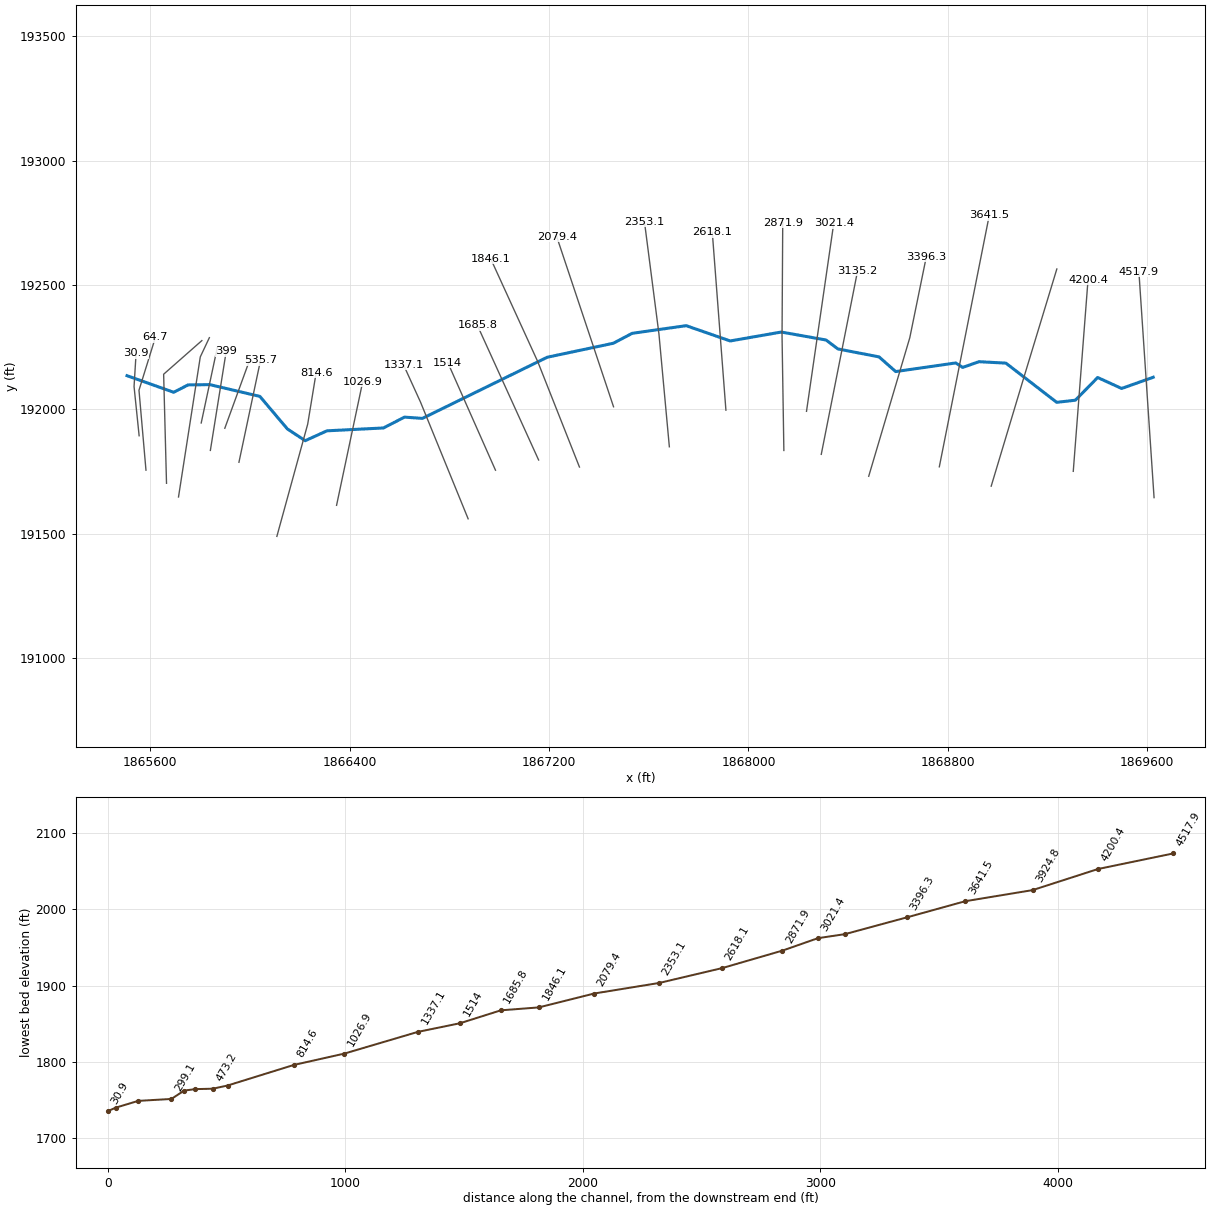
--- NP1600.prj (project) ---

Proj Title=NP1600
Current Plan=p01
Default Exp/Contr=0,0
English Units
Geom File=g01
Flow File=f01
Plan File=p01
BEGIN DESCRIPTION:
END DESCRIPTION:
DSS Export Rating Curves= 0
DSS Export Rating Curve Sorted= 0
DSS Export Volume Flow Curves= 0
DXF OffsetX= 0
DXF OffsetY= 0
DXF ScaleX= 0
DXF ScaleY= 0

--- NP1600.p01 (plan) ---

Plan Title=Floodplain
Program Version=4.00
Geom File=g01
Flow File=f01
K Sum by GR=0
Std Step Tol=0.01
Critical Tol=0.01
Num of Std Step Trials=20
Max Error Tol=0.3
Flow Tol Ratio=0.001
Split Flow NTrial=30
Split Flow Tol=0.02
Split Flow Ratio=0.02
Log Output Level=0
Friction Slope Method=1
Unsteady Friction Slope Method=2
Unsteady Bridges Friction Slope Method=1
Global Log Level=0
CheckData=False
Run HTab=0
Run UNet=0
Run PostProcess=0
UNET Theta=0
UNET Theta Warmup=0
UNET ZTol=0
UNET ZSATol=0
UNET MxIter=0
UNET MaxInSteps=0
UNET DtIC=0
UNET DtMin=0
UNET MaxCRTS=0
UNET WFStab=0
UNET SFStab=0
UNET WFX=0
UNET SFX=0
UNET DSS MLevel=0
UNET DZMax Abort=0
UNET Convert EG Bridges=0
UNET Use Existing IB Tables=0
UNET Froude Limit=0
UNET Froude Power=0
Write IC File=0
Echo Input=False
Echo Output=False
Write Detailed=0

--- NP1600.f01 (steady flow) ---

Flow Title=NFF Regression Equation
Program Version=4.00
Number of Profiles=1
Profile Names=P100yr
River Rch & RM=NP1600,Main      ,4517.9
593.6478
River Rch & RM=NP1600,Main      ,3021.4
630.7514
River Rch & RM=NP1600,Main      ,299.1
690.4828
Boundary for River Rch & Prof#=NP1600,Main      ,1
Up Type=0
Dn Type=3
Dn Slope=0.083089

--- NP1600.g01 (geometry) ---

Geom Title=USGS 10m DEM
Program Version=4.00

River Reach=NP1600          ,Main
Reach XY= 30
     1869623.586      192129.614     1869496.781      192084.464
     1869400.716      192128.654     1869311.375      192037.392
     1869236.445      192028.747     1869032.787      192186.293
     1868924.715      192192.217     1868859.391      192169.161
     1868831.211      192187.093     1868590.409       192152.51
     1868523.804       192211.43     1868358.572      192243.452
      1868311.18      192279.316     1868131.859      192311.337
     1867926.778      192275.511     1867750.162      192336.955
     1867533.696      192306.214     1867457.872      192266.231
     1867192.953      192210.066     1866692.167      191964.223
     1866620.439      191969.346     1866535.902      191925.797
     1866309.189      191914.269      1866222.09      191874.563
     1866150.362      191921.955     1866040.208      192052.603
     1865839.111      192099.995     1865752.013      192098.714
     1865694.374      192069.254     1865507.272      192135.908

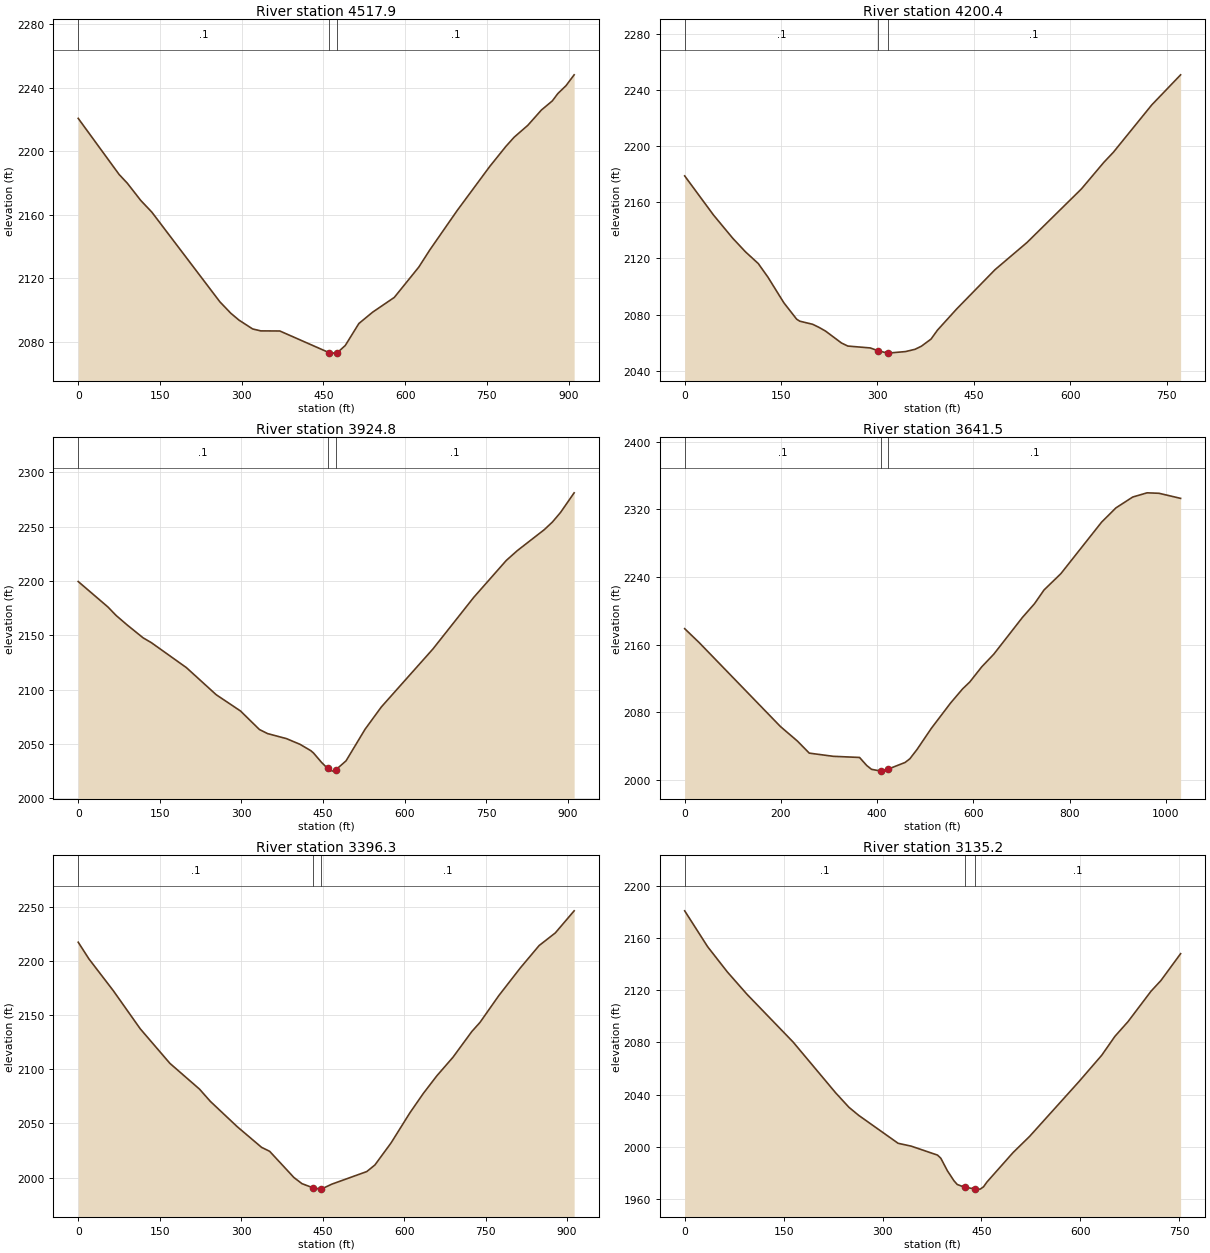
Type RM Length L Ch R = 1 ,4517.9  ,332,317.5,307.7
XS GIS Cut Line= 3
     1869626.902      191645.662     1869596.476      192099.643
      1869566.05      192553.625
#Sta/Elev= 30
       0 2220.75      75 2185.47      90 2179.98     115    2169     135 2161.77
     260 2105.26     280 2098.09     295 2093.76     320 2088.21     335 2086.98
     370 2086.91   460.7 2073.22     470 2072.98   475.7 2073.34     490 2077.77
     515 2091.62     540  2098.7     580 2108.05     625 2127.16     645 2137.86
     695 2162.57     755 2190.42     785 2203.21     800 2208.92     825 2216.38
     850 2226.03     870 2231.76     880 2236.34     895 2241.31     910 2248.16
#Mann= 3 , 0 , 0
       0      .1       0   460.7    .045       0   475.7      .1       0
Bank Sta=460.7,475.7
XS Rating Curve= 0 ,0
Exp/Cntr=0.3,0.1

Type RM Length L Ch R = 1 ,4200.4  ,268.4,275.6,278
XS GIS Cut Line= 2
       1869302.8      191751.432     1869361.991      192520.915
#Sta/Elev= 30
       0 2178.69    44.8 2150.88    74.7 2134.37    94.6 2124.66   114.5 2116.33
   129.5 2106.68   154.4 2088.36   174.3  2076.7   179.2 2075.28   199.2 2073.08
   209.1 2070.88   219.1 2068.29     244 2059.78   253.9 2057.59   288.8 2056.25
   301.2 2054.21   316.2 2052.56   343.6 2053.66   358.5 2055.28   368.4 2057.49
   383.4 2062.56   393.4 2068.92   423.2 2083.95     483 2111.96   532.8 2131.32
   617.4 2169.41   652.3 2188.32   667.2 2195.54   726.9 2229.21   771.8 2250.62
#Mann= 3 , 0 , 0
       0      .1       0   301.2    .045       0   316.2      .1       0
Bank Sta=301.2,316.2
XS Rating Curve= 0 ,0
Exp/Cntr=0.3,0.1

Type RM Length L Ch R = 1 ,3924.8  ,282.4,283.3,284.5
XS GIS Cut Line= 3
     1868973.632      191691.848     1869105.015      192130.051
     1869236.901      192564.819
#Sta/Elev= 30
       0 2199.51    54.7 2176.05    69.6 2168.31    89.5 2159.74   119.3 2147.67
   134.3 2143.29   198.9 2120.25   253.6 2095.33   298.4 2080.31   333.2 2063.24
   348.1 2059.51   382.9 2054.86   407.8 2049.62   427.6 2043.79   432.6 2041.65
   447.5 2032.91   458.6  2027.4   467.5 2024.94   473.6 2026.15   492.4 2034.39
   527.4  2063.5   557.3 2084.01   652.2 2137.44   727.1 2184.87     787 2218.92
     807 2227.84   856.9 2247.27   871.9 2254.32   886.8 2263.14   911.8 2281.19
#Mann= 3 , 0 , 0
       0      .1       0   458.6    .045       0   473.6      .1       0
Bank Sta=458.6,473.6
XS Rating Curve= 0 ,0
Exp/Cntr=0.3,0.1

Type RM Length L Ch R = 1 ,3641.5  ,247.1,245.1,243.2
XS GIS Cut Line= 2
     1868765.527      191769.644     1868965.866      192780.445
#Sta/Elev= 30
       0 2178.97    29.9 2162.62   199.1 2063.12     234 2046.14   258.9 2031.72
   308.6 2027.97   363.4 2026.59   378.3 2017.07   388.3 2012.54   408.2 2010.43
   423.2 2012.92     458 2020.68   467.9 2025.04   482.9 2036.13   512.7 2061.18
   552.6 2091.08   577.5 2107.73   592.4 2115.89   617.3 2133.85   642.2 2148.72
   701.9 2192.32   726.8 2208.44   746.7 2224.76   781.6    2244   866.2 2304.92
     896 2321.83   930.9 2334.69   960.8 2339.68   985.7 2339.13  1030.5 2333.12
#Mann= 3 , 0 , 0
       0      .1       0   408.2    .045       0   423.2      .1       0
Bank Sta=408.2,423.2
XS Rating Curve= 0 ,0
Exp/Cntr=0.3,0.1

Type RM Length L Ch R = 1 ,3396.3  ,258.8,261.2,263.6
XS GIS Cut Line= 3
     1868482.328      191731.645     1868647.145      192288.704
      1868713.42       192614.16
#Sta/Elev= 30
       0 2217.33    19.9 2201.81    64.6 2172.58   114.2 2137.38   168.8 2105.49
   223.4 2081.65   243.3 2070.35     293  2046.9   337.6 2027.92   352.5 2024.25
   397.2 2000.04   412.1 1994.36   432.9 1990.45   446.9 1989.34   447.9 1989.46
   466.7 1993.89   531.3 2005.56   546.2 2011.61     576    2032   610.7 2059.81
   635.5 2077.76   660.2 2093.91     690 2111.11   724.7 2134.87   739.6  2143.2
   774.3 2167.96   813.9 2193.52   848.6 2214.24   878.4 2225.91   913.1 2246.31
#Mann= 3 , 0 , 0
       0      .1       0   432.9    .045       0   447.9      .1       0
Bank Sta=432.9,447.9
XS Rating Curve= 0 ,0
Exp/Cntr=0.3,0.1

Type RM Length L Ch R = 1 ,3135.2  ,112.8,113.8,114.9
XS GIS Cut Line= 2
     1868291.999      191819.729       1868437.7       192557.34
#Sta/Elev= 30
       0 2181.09    34.8 2153.54    64.7 2134.15    94.6 2116.92   164.3 2080.36
     229 2041.24     249 2030.21   263.9 2023.97   323.6 2002.54   343.6 2000.33
   383.4 1993.46   388.4 1991.02   398.3 1981.45   408.3 1973.74   413.3 1970.89
   424.8 1968.72   439.8 1967.56   443.2 1967.34   448.1 1967.36   453.1 1969.12
   458.1 1972.71   497.9 1995.44   522.8 2007.76   597.5 2049.76   632.4 2070.22
   652.3 2084.69   672.2 2096.01     707 2119.33     722 2127.53   751.9 2148.18
#Mann= 3 , 0 , 0
       0      .1       0   424.8    .045       0   439.8      .1       0
Bank Sta=424.8,439.8
XS Rating Curve= 0 ,0
Exp/Cntr=0.3,0.1

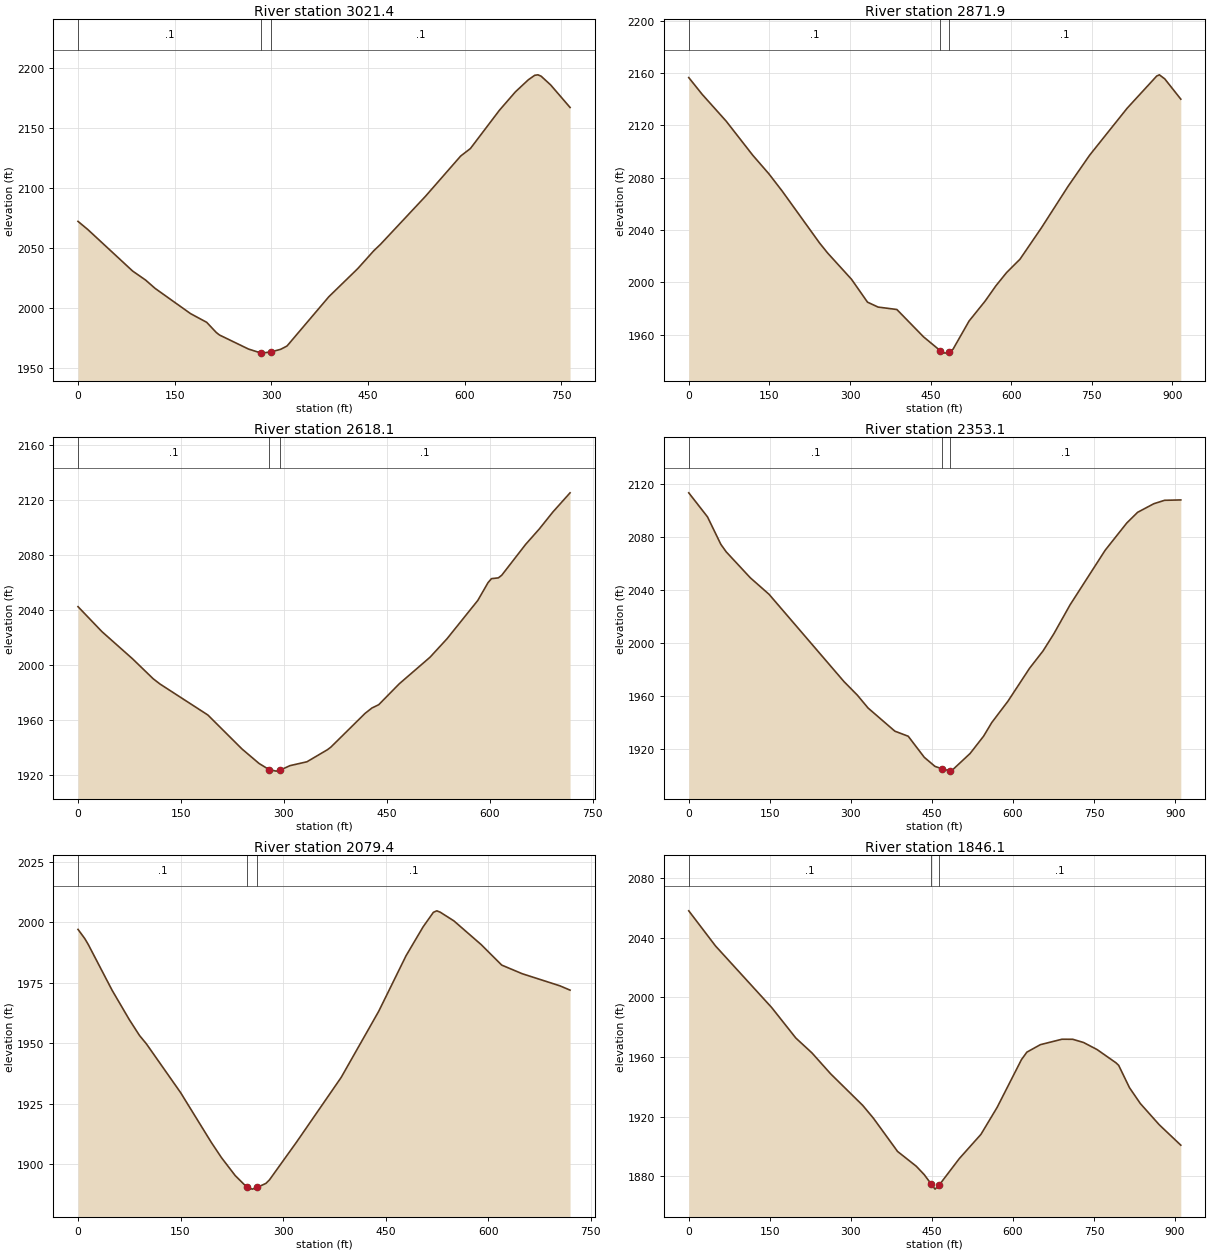
Type RM Length L Ch R = 1 ,3021.4  ,147.1,149.5,151.7
XS GIS Cut Line= 2
     1868232.808      191992.749     1868342.084      192748.573
#Sta/Elev= 30
       0 2071.81      15 2065.12    84.8 2030.42   104.8 2022.96   119.8 2015.93
   174.7 1994.95   199.7 1987.73   214.6 1979.25   219.6 1977.15   264.5 1965.48
   284.4 1962.07   284.5 1962.06   299.4 1963.05   314.5 1965.22   324.4    1968
   389.3 2009.04   434.2 2032.48   459.2 2047.44   469.2 2052.54   539.1 2092.61
     594  2126.3     609 2132.48   653.9 2164.28   678.8 2179.68   698.8 2189.71
   708.8  2193.5   713.8  2193.9   718.8 2192.76   733.7 2185.41   763.7 2166.71
#Mann= 3 , 0 , 0
       0      .1       0   284.4    .045       0   299.4      .1       0
Bank Sta=284.4,299.4
XS Rating Curve= 0 ,0
Exp/Cntr=0.3,0.1

Type RM Length L Ch R = 1 ,2871.9  ,252,253.8,257.1
XS GIS Cut Line= 3
      1868141.97      191835.262     1868134.662      192296.851
     1868137.446      192750.664
#Sta/Elev= 30
       0 2156.44    24.8  2143.7    69.5 2123.19   119.1 2097.06   148.9 2082.95
   173.7 2069.75   243.2 2030.07   258.1 2022.45   302.8 2002.24   332.6 1984.73
   352.4 1980.98   387.2 1979.13   436.8 1958.24   468.3 1947.52   476.6 1945.78
   483.3 1946.58   491.6  1948.7   521.5 1970.29   551.4 1985.56   571.4 1997.22
   591.3 2007.36   616.2 2017.55   656.1 2041.55     706 2073.47   745.9 2097.13
   815.7 2133.04   870.6  2157.6   875.6 2158.55   885.6 2155.47   915.5 2139.95
#Mann= 3 , 0 , 0
       0      .1       0   468.3    .045       0   483.3      .1       0
Bank Sta=468.3,483.3
XS Rating Curve= 0 ,0
Exp/Cntr=0.3,0.1

Type RM Length L Ch R = 1 ,2618.1  ,264.3,264.9,264.4
XS GIS Cut Line= 2
     1867909.534      191997.302     1867854.896      192712.148
#Sta/Elev= 30
       0 2042.57    34.8 2024.43    79.7 2004.51   109.5 1990.12   119.5 1986.27
   189.2 1963.74     239 1938.98   263.9 1928.44   278.6 1923.97   288.8 1922.91
   293.6 1923.43   308.7 1926.88   333.6 1929.73   363.4 1938.49   368.4 1940.38
   418.2 1964.91   428.2 1968.83   438.1 1971.23     468 1986.43   512.8 2005.75
   537.7 2019.27   582.5 2047.13   597.4 2060.07   602.4 2062.96   612.4 2063.52
   617.4 2065.47   652.2  2087.9   672.1 2099.12     692 2111.54   716.9  2125.4
#Mann= 3 , 0 , 0
       0      .1       0   278.6    .045       0   293.6      .1       0
Bank Sta=278.6,293.6
XS Rating Curve= 0 ,0
Exp/Cntr=0.3,0.1

Type RM Length L Ch R = 1 ,2353.1  ,269,273.7,278.3
XS GIS Cut Line= 3
     1867682.626      191850.139     1867640.882      192303.867
     1867582.743      192755.023
#Sta/Elev= 30
       0 2113.02    34.7  2094.9    59.4 2074.21    69.3 2068.57   113.9 2049.04
   148.6  2036.6   287.2  1970.9     312 1960.66   331.8 1950.98   381.4 1933.54
   406.1 1929.73   435.8 1913.86   455.6 1907.03   468.9 1905.18   483.9 1903.57
   485.6 1903.46   520.6 1916.75   545.6  1929.8   560.6 1939.98   590.6  1956.1
   630.6  1980.9   655.6 1993.98   675.6 2006.92   705.6 2028.68   770.6 2069.82
   810.6 2090.35   830.6 2098.35   860.5  2104.8   880.5 2107.39   910.5 2107.67
#Mann= 3 , 0 , 0
       0      .1       0   468.9    .045       0   483.9      .1       0
Bank Sta=468.9,483.9
XS Rating Curve= 0 ,0
Exp/Cntr=0.3,0.1

Type RM Length L Ch R = 1 ,2079.4  ,232.4,233.3,235.3
XS GIS Cut Line= 2
     1867458.772      192010.962     1867231.114      192693.935
#Sta/Elev= 30
       0 1997.05      10 1993.21      15  1990.8      50 1971.82      75 1959.76
      90 1953.17     100 1949.74     150  1929.6     195 1908.98     210 1902.62
     230 1895.25   247.3 1890.38     255 1889.65   262.3 1890.37     275 1892.04
     280 1893.44     320 1909.21     385 1935.84     440 1963.22   479.9 1986.14
   504.9 1998.11   519.9  2004.1   524.9 2004.73   529.9 2004.17   549.9 2000.58
   589.9 1990.75   619.9 1982.29   649.9 1978.72   704.9 1973.73   719.9 1971.94
#Mann= 3 , 0 , 0
       0      .1       0   247.3    .045       0   262.3      .1       0
Bank Sta=247.3,262.3
XS Rating Curve= 0 ,0
Exp/Cntr=0.3,0.1

Type RM Length L Ch R = 1 ,1846.1  ,159.2,160.3,160.2
XS GIS Cut Line= 3
      1867322.03      191768.688     1867154.684      192192.603
     1866965.852      192606.423
#Sta/Elev= 30
       0 2058.05    49.5  2034.5   153.6 1993.15   198.2 1972.74   227.9 1962.82
   262.6 1948.76     322 1927.58   341.8 1918.98   386.4 1896.73   421.1 1886.79
   435.9 1881.12   448.3 1875.04   455.8 1871.46   463.3 1874.13   500.7 1891.94
   540.7 1908.17   570.7 1926.28   615.7 1958.29   625.7  1963.3   650.7 1968.32
   690.7 1971.96   710.7 1971.92   730.7 1969.76   755.7 1965.02   790.6 1956.16
   795.6 1954.46   815.6 1939.48   835.6 1928.89   870.6 1914.65   910.6 1900.92
#Mann= 3 , 0 , 0
       0      .1       0   448.3    .045       0   463.3      .1       0
Bank Sta=448.3,463.3
XS Rating Curve= 0 ,0
Exp/Cntr=0.3,0.1

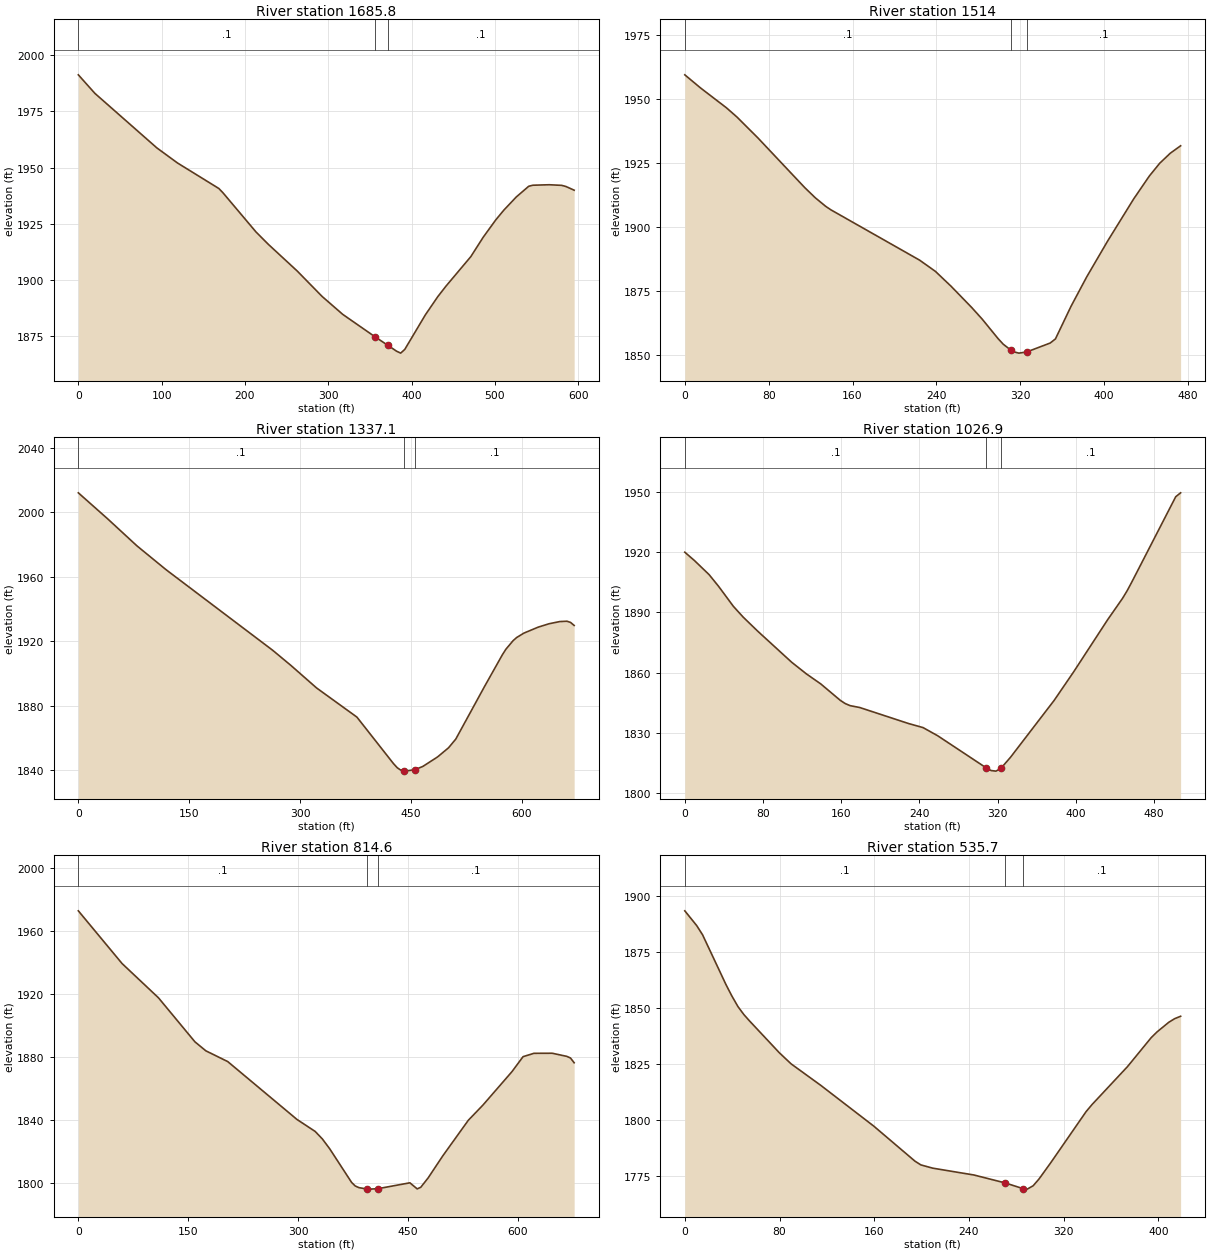
Type RM Length L Ch R = 1 ,1685.8  ,173.2,171.8,171.6
XS GIS Cut Line= 2
     1867158.264      191796.963     1866912.393      192338.789
#Sta/Elev= 30
       0  1991.2    19.8 1982.99    94.2 1958.76     119 1952.05   168.6 1940.72
   173.5 1938.84   213.2 1921.42   228.1 1915.89   262.8 1904.02   292.5 1892.79
   317.3 1884.81   356.4 1874.76   371.4 1871.08   381.8 1868.48   386.8  1867.6
   391.7 1869.23   416.5 1884.63   431.4  1892.7   441.3  1897.4     471 1910.46
   485.9 1919.09   500.8 1926.71   510.7 1931.14   525.6 1936.97   540.5 1941.71
   545.4 1942.17   565.2 1942.38   580.1 1942.11   585.1 1941.61     595 1939.96
#Mann= 3 , 0 , 0
       0      .1       0   356.4    .045       0   371.4      .1       0
Bank Sta=356.4,371.4
XS Rating Curve= 0 ,0
Exp/Cntr=0.3,0.1

Type RM Length L Ch R = 1 ,1514    ,175.7,177,175.7
XS GIS Cut Line= 2
     1866985.244      191755.985     1866794.011      192188.535
#Sta/Elev= 30
       0 1959.28    14.9  1954.2    39.8 1946.39    49.8  1942.8    69.7 1934.68
   114.5 1915.24   124.5  1911.3   134.4 1907.97   139.4  1906.6     224 1886.97
     239 1882.61   253.9 1876.83   273.8 1868.44   283.8  1863.9   298.7 1856.42
   303.7  1854.2     311 1851.88   313.6 1851.24   318.6 1850.71     326 1851.15
   348.5 1854.65   353.5 1856.25   368.4 1868.99   383.3 1880.43   403.2 1894.37
   428.1 1910.85   443.1 1919.82     453  1924.8     463 1928.68   472.9  1931.6
#Mann= 3 , 0 , 0
       0      .1       0     311    .045       0     326      .1       0
Bank Sta=311,326
XS Rating Curve= 0 ,0
Exp/Cntr=0.3,0.1

Type RM Length L Ch R = 1 ,1337.1  ,324.6,310.2,297.3
XS GIS Cut Line= 3
     1866875.546      191560.607     1866684.736      192029.174
     1866616.438      192179.428
#Sta/Elev= 30
       0 2012.03    39.7 1995.89    79.4 1979.11     119 1964.26   262.9 1914.42
   287.7 1904.98   322.4 1891.02     377 1872.94   426.6 1844.03   431.5 1841.57
   436.5 1839.98   440.1 1839.58   441.4 1839.43   455.1 1840.28   466.2 1842.34
   486.1 1848.21     501  1853.9   510.8  1859.3   549.6 1891.82   573.9 1911.62
   578.7 1915.08   588.4 1920.35   593.3 1922.32     603 1925.03   622.4 1928.74
     637 1930.83   651.6 1932.19   661.3  1932.4   666.1 1931.66     671 1929.78
#Mann= 3 , 0 , 0
       0      .1       0   440.1    .045       0   455.1      .1       0
Bank Sta=440.1,455.1
XS Rating Curve= 0 ,0
Exp/Cntr=0.3,0.1

Type RM Length L Ch R = 1 ,1026.9  ,213.6,212.3,210.9
XS GIS Cut Line= 2
     1866347.802      191614.837     1866452.525      192111.131
#Sta/Elev= 30
       0 1919.88      10 1915.66    24.9  1908.7    34.8 1902.74    49.7 1892.94
    59.7 1887.59    74.6 1880.58   109.4  1865.1   124.3 1859.37   139.2  1854.3
   159.1 1846.16   164.1 1844.57   169.1 1843.54     179  1842.6   228.8 1834.65
   243.7 1832.62   258.6 1828.59   308.4 1812.56   313.3 1811.25   318.3 1810.96
   323.4 1812.37   333.2 1817.86   377.9  1846.2   397.8 1860.36   432.6 1886.32
   447.6 1896.78   452.5 1900.69   457.5 1905.25   502.2 1947.47   507.2 1949.41
#Mann= 3 , 0 , 0
       0      .1       0   308.4    .045       0   323.4      .1       0
Bank Sta=308.4,323.4
XS Rating Curve= 0 ,0
Exp/Cntr=0.3,0.1

Type RM Length L Ch R = 1 ,814.6   ,291.6,278.9,279.9
XS GIS Cut Line= 3
     1866108.347      191490.005     1866231.984         191941.
     1866265.845      192147.556
#Sta/Elev= 30
       0 1972.86    59.7  1939.4   109.4 1917.64   159.2 1889.68   174.1 1883.97
     204 1877.13   298.5  1840.4   323.4 1832.77   333.3 1827.95   343.3 1821.71
   373.1 1800.42   378.1 1798.13   383.1 1797.09   394.3 1796.18     398 1796.14
   409.3 1796.43   452.7 1800.16   462.7 1796.28   467.6 1797.34   477.6 1803.24
   497.5 1817.17   532.4 1839.81   552.4 1849.48   592.2  1870.8   607.2 1880.24
   622.1 1882.38     647 1882.43     667 1880.44     672 1879.39     677 1876.39
#Mann= 3 , 0 , 0
       0      .1       0   394.3    .045       0   409.3      .1       0
Bank Sta=394.3,409.3
XS Rating Curve= 0 ,0
Exp/Cntr=0.3,0.1

Type RM Length L Ch R = 1 ,535.7   ,65.7,62.5,59.3
XS GIS Cut Line= 2
     1865956.231      191787.857     1866042.741      192197.641
#Sta/Elev= 30
       0 1893.44      10 1886.89      15 1882.76    34.9 1860.39    39.9 1855.29
    44.9  1850.7    49.9 1847.13    54.8 1844.23    79.8 1830.12    89.8 1825.13
   114.7  1815.6   159.6 1797.35   194.4 1781.71   199.4 1780.03   209.4 1778.58
   244.3 1775.52   270.8 1771.96   285.8 1769.42   289.2 1769.22   294.2  1770.7
   299.2 1773.75   309.1    1781     339 1803.85     344 1806.98   373.9 1823.89
   393.9  1836.8   398.9  1839.4   408.8 1843.69   413.8 1845.31   418.8 1846.38
#Mann= 3 , 0 , 0
       0      .1       0   270.8    .045       0   285.8      .1       0
Bank Sta=270.8,285.8
XS Rating Curve= 0 ,0
Exp/Cntr=0.3,0.1

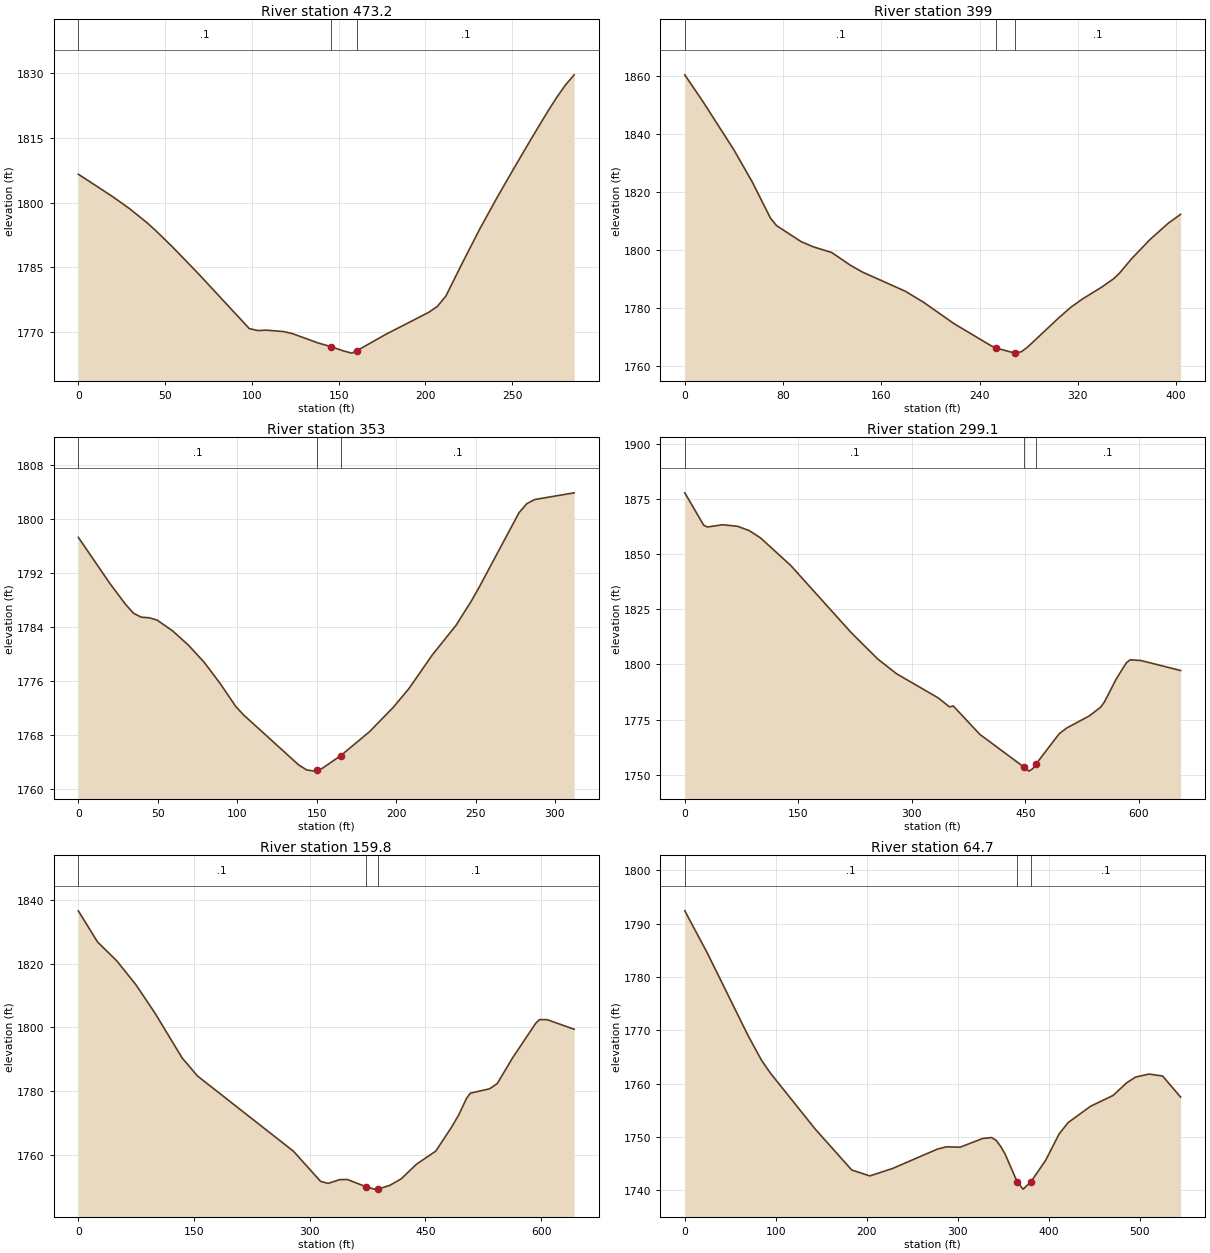
Type RM Length L Ch R = 1 ,473.2   ,69.5,74.1,78.8
XS GIS Cut Line= 2
     1865899.536      191924.564     1865997.045      192193.068
#Sta/Elev= 30
       0  1806.6    19.7 1801.41    29.6 1798.58    39.4 1795.39    44.3 1793.62
    54.2 1789.74      69 1783.58    98.5 1770.76   103.4  1770.3   108.4 1770.39
   118.2 1770.07   123.1 1769.62   137.9 1767.46   145.7 1766.54   152.7 1765.58
   157.6 1765.06   160.7 1765.67   177.3 1769.45   201.9 1774.53   206.9 1775.91
   211.8 1778.33   221.6 1786.25   231.5 1794.03   241.3 1801.19   251.2 1808.11
     261 1814.84   270.9 1821.44   275.8 1824.52   280.7 1827.31   285.7 1829.67
#Mann= 3 , 0 , 0
       0      .1       0   145.7    .045       0   160.7      .1       0
Bank Sta=145.7,160.7
XS Rating Curve= 0 ,0
Exp/Cntr=0.3,0.1

Type RM Length L Ch R = 1 ,399     ,47.4,46,44.6
XS GIS Cut Line= 2
     1865841.596      191835.534     1865905.189       192234.05
#Sta/Elev= 30
       0 1860.25      15  1850.9    39.9 1834.49    54.8 1823.48    69.8  1810.9
    74.7 1808.37    94.7 1802.86   104.6 1801.07   119.6 1799.12   134.5 1794.82
   144.5 1792.41   179.4 1785.81   194.3 1782.01   219.2 1774.63   249.1 1767.09
   253.5 1766.22   268.5 1764.55     269  1764.5     274 1764.99     279 1766.56
   303.9 1776.44   313.9 1780.18   323.8 1783.16   338.8 1787.05   348.8    1790
   353.7 1791.94   363.7 1796.98   378.6 1803.56   393.6 1809.21   403.6 1812.25
#Mann= 3 , 0 , 0
       0      .1       0   253.5    .045       0   268.5      .1       0
Bank Sta=253.5,268.5
XS Rating Curve= 0 ,0
Exp/Cntr=0.3,0.1

Type RM Length L Ch R = 1 ,353     ,52.7,54,55.2
XS GIS Cut Line= 2
     1865804.854      191945.762      1865869.86      192251.008
#Sta/Elev= 30
       0 1797.27    19.8 1790.45    29.7 1787.34    34.7 1786.02    39.6 1785.43
    44.6 1785.34    49.5 1785.01    59.4 1783.39    69.4 1781.26    79.3 1778.72
    89.2 1775.62    99.1 1772.19     104 1770.94   138.7 1763.52   143.7 1762.78
   148.6  1762.6   150.2 1762.73   153.6 1763.02   165.2  1764.9   183.3 1768.45
   198.2 1772.05   208.1 1774.84   222.9 1779.86   237.8 1784.24   247.7 1787.95
   252.6 1789.99   277.4 1800.93   282.4 1802.28   287.3 1802.88   312.1 1803.87
#Mann= 3 , 0 , 0
       0      .1       0   150.2    .045       0   165.2      .1       0
Bank Sta=150.2,165.2
XS Rating Curve= 0 ,0
Exp/Cntr=0.3,0.1

Type RM Length L Ch R = 1 ,299.1   ,134.1,139.3,144.5
XS GIS Cut Line= 3
     1865713.799      191648.333     1865801.137        192211.3
     1865837.562      192288.704
#Sta/Elev= 30
       0 1877.74      25 1863.05      30 1862.26      50 1863.28      70 1862.56
      85 1860.64     100 1857.34   139.9 1844.86   219.9 1814.39   254.9 1802.47
   279.8 1795.77   334.8 1784.84   349.8 1780.75   354.8 1781.16   389.8 1768.32
   448.7 1753.34   454.8 1751.64   459.8 1752.74   463.7 1754.68   494.7 1768.56
   504.7 1771.18   534.7 1776.69   549.7 1780.68   554.7 1783.08   569.7 1793.13
   579.2 1798.43     584  1800.9   588.7  1802.1     603 1801.74   655.2 1797.23
#Mann= 3 , 0 , 0
       0      .1       0   448.7    .045       0   463.7      .1       0
Bank Sta=448.7,463.7
XS Rating Curve= 0 ,0
Exp/Cntr=0.3,0.1

Type RM Length L Ch R = 1 ,159.8   ,103.4,95.1,86.8
XS GIS Cut Line= 3
     1865665.695       191703.38     1865654.159      192141.758
     1865807.426      192276.897
#Sta/Elev= 30
       0  1836.6    24.9 1826.82    49.8  1820.9    74.8 1813.33    99.7 1804.34
   134.6 1790.37   154.5  1784.7   279.1 1761.02     314  1751.6   323.9 1750.94
   338.9 1752.12   348.8 1752.17   373.2 1749.87   383.7 1749.14   388.2 1749.15
   403.6 1750.29   418.6 1752.36   438.5 1756.98   463.4 1761.07   483.4 1768.41
   493.4 1772.53   503.3 1777.65   508.3 1779.29   533.2 1780.66   543.2 1782.34
   563.1  1790.4     593 1801.25     598 1802.42     608 1802.39   642.9 1799.38
#Mann= 3 , 0 , 0
       0      .1       0   373.2    .045       0   388.2      .1       0
#XS Ineff= 2 , 0
          343.91  1751.9
Permanent Ineff=
       F       F
Bank Sta=373.2,388.2
XS Rating Curve= 0 ,0
Exp/Cntr=0.3,0.1

Type RM Length L Ch R = 1 ,64.7    ,28.2,33.8,39.3
XS GIS Cut Line= 3
     1865583.293      191756.117     1865555.277      192077.485
     1865621.198      192290.081
#Sta/Elev= 30
       0  1792.4    24.8 1784.48    69.5 1769.04    84.4 1764.38    94.3 1761.94
   143.9 1751.39   183.6 1743.81   203.5 1742.71   228.3 1744.09   277.9 1747.74
   287.8 1748.17   302.7 1748.09   327.5 1749.72   337.4  1749.9   342.4 1749.36
   347.3 1748.25   352.3 1746.77   365.6 1741.56     372 1740.23   380.6  1741.6
   396.8 1745.64   411.6 1750.57   421.5  1752.7   446.2 1755.77     471  1757.8
   485.8 1760.15   495.7 1761.24   510.5  1761.8   525.4 1761.43   545.2 1757.48
#Mann= 3 , 0 , 0
       0      .1       0   365.6    .045       0   380.6      .1       0
#XS Ineff= 2 , 0
          337.55 1749.74
Permanent Ineff=
       F       F
Bank Sta=365.6,380.6
XS Rating Curve= 0 ,0
Exp/Cntr=0.3,0.1

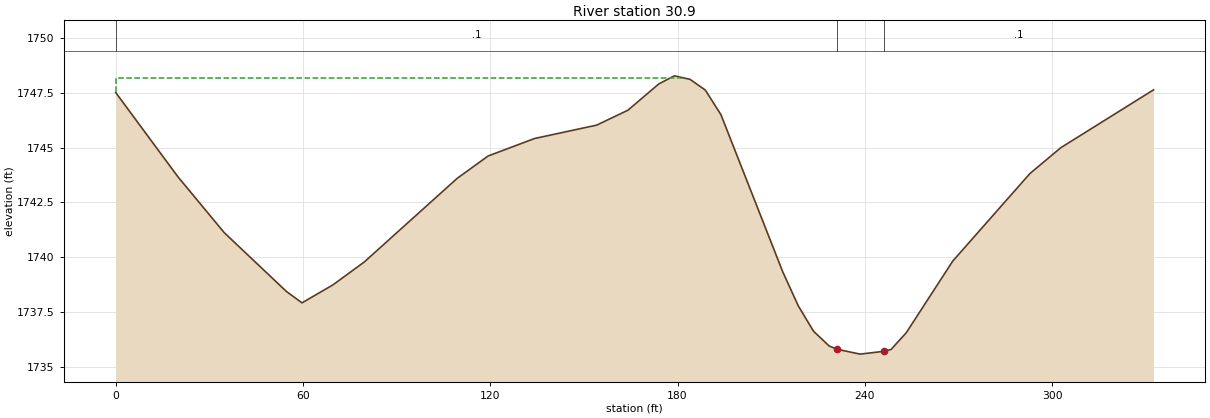
Type RM Length L Ch R = 1 ,30.9    ,33,30.9,28.9
XS GIS Cut Line= 3
     1865555.839      191894.457     1865535.499        192092.3
     1865543.636      192225.686
#Sta/Elev= 30
       0 1747.52    19.9 1743.68    34.8 1741.12    54.7 1738.44    59.7 1737.92
    69.6 1738.74    79.6 1739.78   109.4  1743.6   119.3 1744.62   134.2 1745.42
   154.1 1746.03   164.1 1746.71     174 1747.91     179 1748.28     184 1748.12
   188.9 1747.63   193.9 1746.51   213.7 1739.34   218.7 1737.78   223.6 1736.62
   228.6 1735.95   231.2  1735.8   238.5 1735.58   246.2 1735.71   248.4 1735.79
   253.3 1736.56   268.2 1739.83   292.9 1743.82   302.8    1745   332.5 1747.64
#Mann= 3 , 0 , 0
       0      .1       0   231.2    .045       0   246.2      .1       0
#XS Ineff= 2 , 0
          182.44 1748.16
Permanent Ineff=
       F       F
Bank Sta=231.2,246.2
XS Rating Curve= 0 ,0
Exp/Cntr=0.3,0.1

Chan Stop Cuts=-1
Use User Specified Reach Order=0